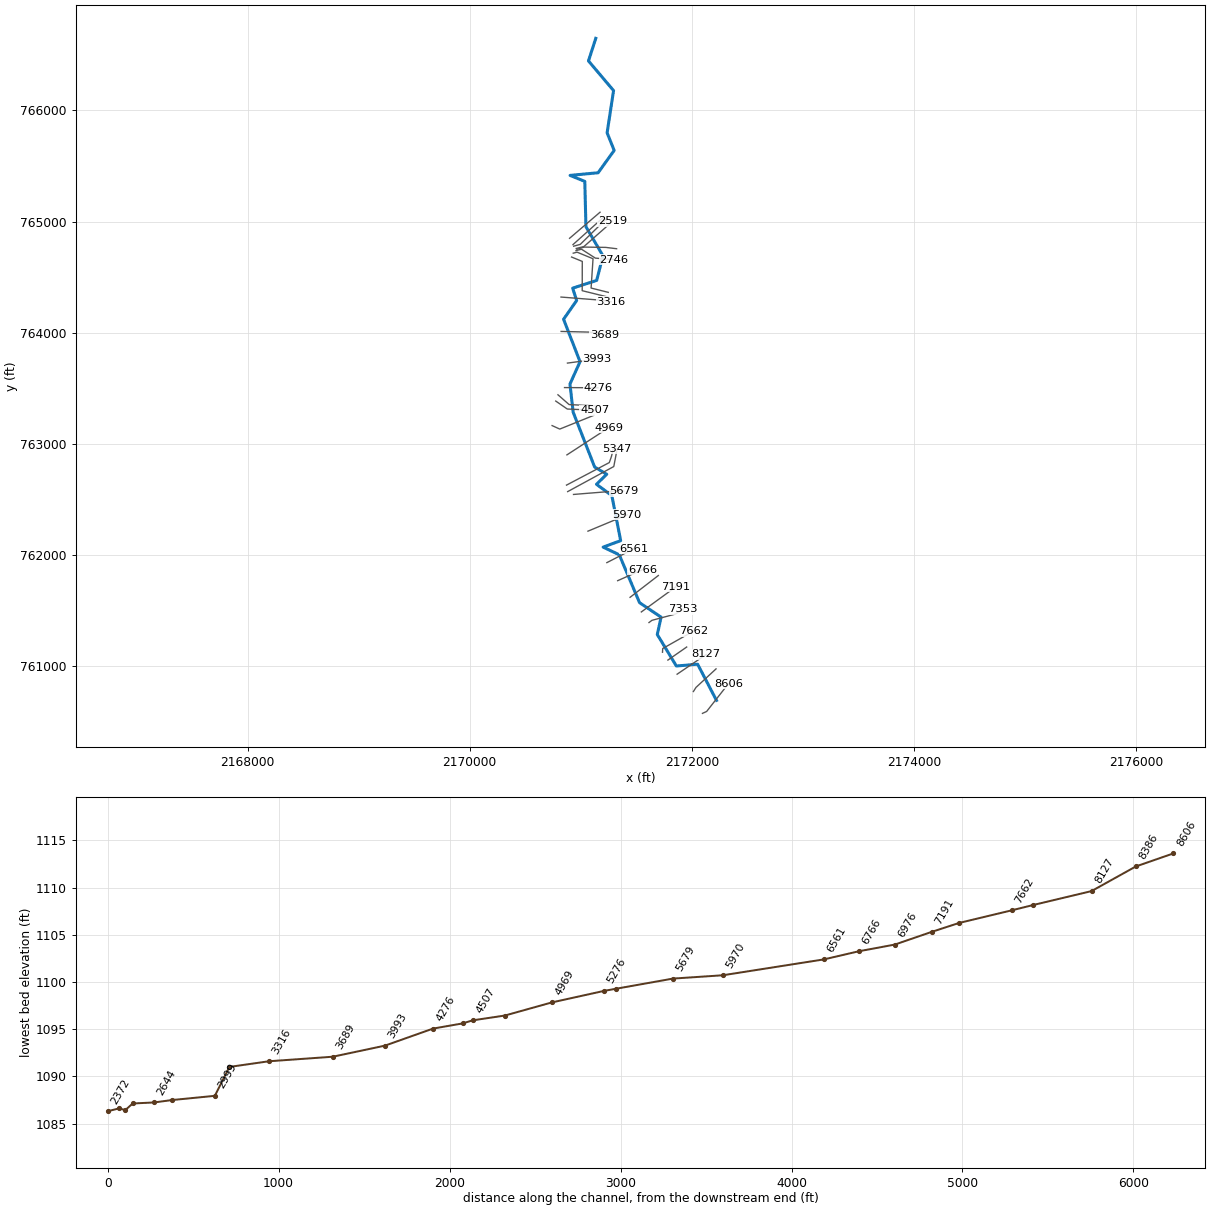
--- ROOTINGCK.prj (project) ---

Proj Title=ROOTINGCK
Current Plan=p01
Default Exp/Contr=0,0
English Units
Geom File=g01
Flow File=f01
Plan File=p01
BEGIN DESCRIPTION:
---------- MODELED AS PART OF WVEMD CTP PROGRAM, 2023----------
Stream Name: Rooting Creek
Flood Zone:  AFH
Upshur County, WV
HEC-RAS Version: RAS 6.3
Vertical Datum: NAVD88
Projection: NAD 1983 StatePlane West Virginia S FIPS 4702 (US Feet)
Terrain: 1-meter LIDAR (FEMA Region III 3DEP collected 2016-2018)
Land Use: 2019 NLCD
Hydrologic Method:
WV SIR2010-5033 regression equations
Additional Model Notes:
None
END DESCRIPTION:
DSS Export Rating Curves= 0
DSS Export Rating Curve Sorted= 0
DSS Export Volume Flow Curves= 0
DXF OffsetX= 0
DXF OffsetY= 0
DXF ScaleX= 0
DXF ScaleY= 0

--- ROOTINGCK.p01 (plan) ---

Plan Title=Floodplain
Program Version=6.30
Short Identifier=Floodplain
Geom File=g01
Flow File=f01
Subcritical Flow
K Sum by GR= 0
Std Step Tol= 0.01
Critical Tol= 0.01
Num of Std Step Trials= 20
Max Error Tol= 0.3
Flow Tol Ratio= 0.001
Split Flow NTrial= 30
Split Flow Tol= 0.02
Split Flow Ratio= 0.02
Log Output Level= 0
Friction Slope Method= 1
Unsteady Friction Slope Method= 2
Unsteady Bridges Friction Slope Method= 1
Parabolic Critical Depth
Global Vel Dist= 0 , 0 , 0
Global Log Level= 0
CheckData=False
Encroach Param=-1 ,0,0, 0
Mapping Interval=1HOUR
Computation Time Step Use Courant=        0
Computation Time Step Use Time Series=    0
Computation Time Step Count To Double=0
Computation Time Step Max Doubling=0
Computation Time Step Max Halving=0
Computation Time Step Residence Courant=0
Run HTab= 0
Run UNet= 0
Run Sediment= 0
Run PostProcess= 0
Run WQNet= 0
Run RASMapper=-1
UNET Theta= 0
UNET Theta Warmup= 0
UNET ZTol= 0
UNET ZSATol= 0
UNET MxIter= 0
UNET Max Iter WO Improvement= 0
UNET MaxInSteps= 0
UNET DtIC= 0
UNET DtMin= 0
UNET MaxCRTS= 0
UNET WFStab= 0
UNET SFStab= 0
UNET WFX= 1
UNET SFX= 1
UNET Gravity=32.17405
UNET 1D Methodology=Finite Difference
UNET DSS MLevel= 1
UNET Pardiso=0
UNET DZMax Abort= 0
UNET Use Existing IB Tables= 0
UNET Froude Reduction=False
UNET Froude Limit= 0
UNET Froude Power= 0
UNET D1 Cores= 0
UNET WindReference=Eulerian
UNET WindDragFormulation=Hsu (1988)
UNET D2 Coriolis=0
UNET D2 Cores= 0
UNET D2 Theta= 1
UNET D2 Theta Warmup= 1
UNET D2 Z Tol= 0.01
UNET D2 Volume Tol= 0.01
UNET D2 Max Iterations= 20
UNET D2 Equation= 0
UNET D2 RampUpFraction=0.1
UNET D2 TimeSlices= 1
UNET D2 Turbulence Formulation=Non-Conservative (original)
UNET D2 Eddy Viscosity=0.3
UNET D2 Transverse Eddy Viscosity=0.1
UNET D2 Smagorinsky Mixing=0
UNET D2 BCVolumeCheck=0
UNET D2 Cores=0
UNET D2 SolverType=PARDISO (Direct)
UNET D2 Minimum Iterations= 3
UNET D2 Maximum Iterations= 30
UNET D2 Restart Number= 10
UNET D2 Relaxation Coeff=1.3
UNET D2 SOR Precondition Iterations= 10
UNET D2 ILUT Maximum Fill= 8
UNET D2 ILUT Tolerance=1E-08
UNET D2 Convergence Tolerance=0.00001
UNET D1D2 MaxIter= 0
UNET D1D2 ZTol=0.01
UNET D1D2 QTol=0.1
UNET D1D2 MinQTol=1
Write IC File= 0
Write IC File at Fixed DateTime=0
Write IC File at Sim End=0
Echo Input=False
Echo Parameters=False
Echo Output=False
Write Detailed= 0
HDF Write Warmup=0
HDF Write Time Slices=0
HDF Flush=0
HDF Compression= 1
HDF Chunk Size= 1
HDF Spatial Parts= 1
HDF Use Max Rows=0
HDF Fixed Rows= 1
Calibration Method= 0
Calibration Iterations= 20
Calibration Max Change=0.05
Calibration Tolerance=0.2
Calibration Maximum=1.5
Calibration Minimum=0.5
Calibration Optimization Method= 1
WQ AD Non Conservative
WQ ULTIMATE=-1
WQ Max Comp Step=1HOUR
WQ Output Interval=15MIN
WQ Output Selected Increments= 0
WQ Output face flow=0
WQ Output face velocity=0
WQ Output face area=0
WQ Output face dispersion=0
WQ Output cell volume=0
WQ Output cell surface area=0
WQ Output cell continuity=0
WQ Output cumulative cell continuity=0
WQ Output face conc=0
WQ Output face dconc_dx=0
WQ Output face courant=0
WQ Output face peclet=0
WQ Output face adv mass=0
WQ Output face disp mass=0
WQ Output cell mass=0
WQ Output cell source sink temp=0
WQ Output nsm pathways=0
WQ Output nsm derived pathways=0
WQ Create Restart=0
WQ Fixed Restart=0
WQ System Summary=0
WQ Write To DSS=0
Sorting and Armoring Iterations= 10
XS Update Threshold= 0.02
Bed Roughness Predictor= 0
Hydraulics Update Threshold= 0.02
Energy Slope Method= 1
Volume Change Method= 1
Sediment Retention Method= 0
Sediment TS Multiplier= 1
Warm Up Method= 0
XS Weighting Method= 0
Number of US Weighted Cross Sections= 1
Number of DS Weighted Cross Sections= 1
Upstream XS Weight=0
Main XS Weight=1
Downstream XS Weight=0
Number of DS XS's Weighted with US Boundary= 1
Upstream Boundary Weight= 1
Weight of XSs Associated with US Boundary= 0
Number of US XS's Weighted with DS Boundary= 1
Downstream Boundary Weight= 0.5
Weight of XSs Associated with DS Boundary= 0.5
Percentile Method= 0
Sediment Output Level= 3
Mass or Volume Output= 0
Output Increment Type= 1
Profile and TS Output Increment= 1
Transport Output Increment 1
XS Output Flag= 0
XS Output Increment= 10
Read HDF5 Sediment Hotstart= 0
Sediment Hotstart Type= 0
Write Gradation File= 0
Read Gradation Hotstart= 0
Write HDF5 File= 1
Write Binary Output= 1
Write DSS Sediment File= 0
DSS Sediment Output Type= 1
SV Curve= 0
Specific Gage Flag= 0
Subcell Erosion Methods= 0
Subcell Deposition Methods= 0
Advection Scheme= 1
Matrix Solver= 0
Implicit Weighting Factor= 1
Maximum Outer Loop Convergence Iterations= 5
Convergence Maximum Absolute= 0.001
Convergence RMSE= 0.0001
Grain Fractions Max Abs Error= 0.001
Max Subgrid Regions= 1
Max Subgrid Length Scale= 3.402823E+38
Initial Layer Thickness= 3.402823E+38
Min Layer Thickness= 3.402823E+38
Max Layer Thickness= 3.402823E+38
Number of Layers= 5

--- ROOTINGCK.f01 (steady flow) ---

Flow Title=Flows
Program Version=6.30
Number of Profiles= 1
Profile Names=01pct
River Rch & RM=ROOTINGCK,Main            ,8606
     706
River Rch & RM=ROOTINGCK,Main            ,5347
     838
River Rch & RM=ROOTINGCK,Main            ,3316
     936
Boundary for River Rch & Prof#=ROOTINGCK,Main            , 1
Up Type= 0
Dn Type= 3
Dn Slope=0.0031
DSS Import GetInterval= 0
DSS Import GetPeak= 0
DSS Import FillOption= 0

--- ROOTINGCK.g01 (geometry) ---

Geom Title=Geometry
Program Version=6.30

River Reach=ROOTINGCK       ,Main
Reach XY= 30
     2172221.178      760688.887     2172051.483      761014.713
     2171860.268      760998.259     2171688.284      761281.905
     2171722.595      761438.293     2171528.605      761568.641
     2171346.318      761999.632     2171200.661      762068.684
     2171358.766      762127.061     2171279.241      762531.897
     2171140.938      762634.487     2171233.255      762724.428
     2171124.369      762789.845     2170931.152      763282.963
     2170902.106      763536.647     2170992.849      763737.906
     2170844.644      764119.964     2170962.343        764288.8
      2170926.63      764399.832     2171142.713      764470.028
     2171199.459      764690.918     2171046.018      764953.301
     2171035.744      765361.228     2170902.964      765415.113
     2171155.619      765438.893     2171300.045      765640.009
     2171236.574      765798.515      2171294.78      766178.369
     2171068.796      766445.6752171134.68009232766649.024463917

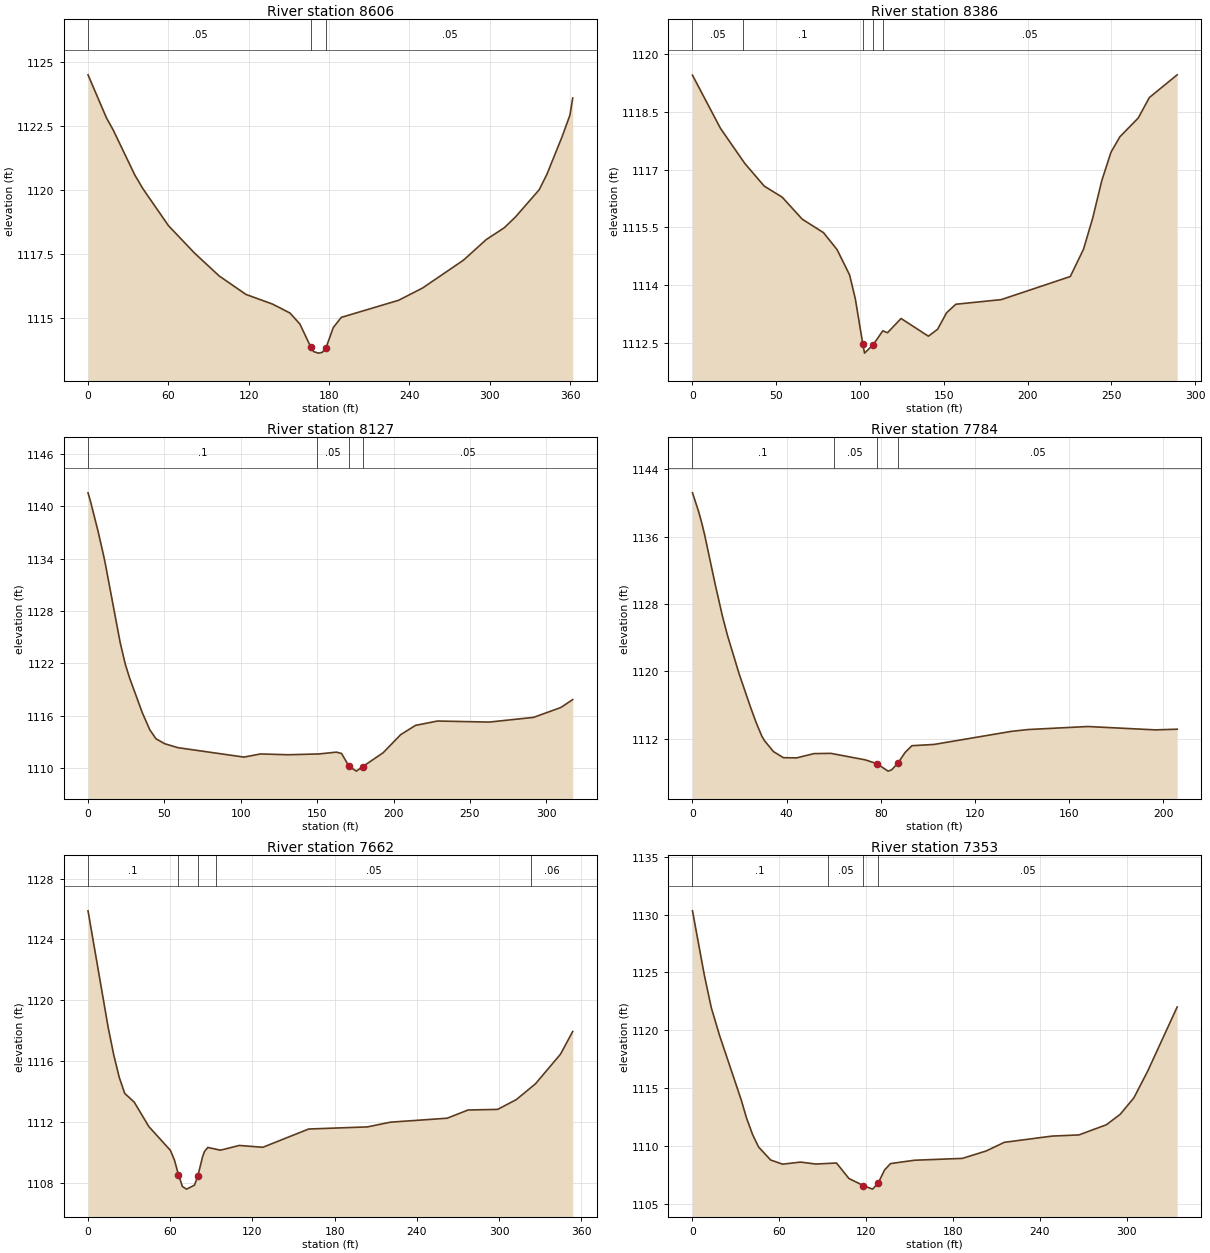
Type RM Length L Ch R = 1 ,8606    ,219.7,219.7,219.7
XS GIS Cut Line= 4
2172095.05356703760571.9959305562172132.44915231760589.081239788
2172307.21818296760811.5731791772172333.70819414 760838.67568023
#Sta/Elev= 30
       0 1124.51    13.8 1122.82    18.8 1122.35    34.9 1120.59    41.1 1120.04
    60.1  1118.6    79.5 1117.53      98 1116.63   117.9 1115.91   137.8 1115.53
   150.8 1115.18   158.2 1114.75   166.41113.841   168.4 1113.67     172 1113.61
   174.9 1113.64   177.7 1113.82   183.1 1114.61   189.1 1115.01   231.9 1115.68
   249.8 1116.16   280.3 1117.25   297.4 1118.06   310.8 1118.52   319.1 1118.94
   336.9 1120.01   342.6 1120.61     354 1122.09   359.8 1122.93   361.9  1123.6
#Mann= 3 ,-1,0
       0     .05       0   166.4    .045       0   177.7     .05       0
Bank Sta=166.4,177.7
XS Rating Curve= 0 ,0
Exp/Cntr(USF)=0,0
Exp/Cntr=0.3,0.1

Type RM Length L Ch R = 1 ,8386    ,257.3,259.5,254
XS GIS Cut Line= 3
 2172013.3923308760768.8771550262172037.03557513760805.895643758
2172217.22274274 760972.50409925
#Sta/Elev= 30
       0 1119.45    16.7 1118.07    31.2 1117.16    42.8 1116.57    53.6 1116.28
    65.5 1115.71    78.2 1115.36    86.3 1114.92    93.8 1114.26    97.2 1113.64
   101.71112.455   102.7 1112.23   107.9 1112.45   113.6 1112.81   116.4 1112.76
   124.5 1113.13   140.8 1112.67   146.3 1112.85   151.7 1113.28   157.2  1113.5
   184.3 1113.62   225.5 1114.22   233.4 1114.93   238.9 1115.74   244.3 1116.71
   249.8 1117.45   255.1 1117.85   266.1 1118.34   272.7 1118.87   289.3 1119.46
#Mann= 5 ,-1,0
       0     .05       0      30      .1       0   101.7    .045       0
   107.9      .1       0  113.92     .05       0
Bank Sta=101.7,107.9
XS Rating Curve= 0 ,0
Exp/Cntr(USF)=0,0
Exp/Cntr=0.3,0.1

Type RM Length L Ch R = 1 ,8127    ,336.1,342.7,334.3
XS GIS Cut Line= 2
2171866.77067821760924.7407092412172129.36007829761102.852054536
#Sta/Elev= 30
       0 1141.56     1.7 1140.53     6.5  1137.2      10 1134.53    11.4 1133.35
      21 1124.42    24.4 1121.89    27.2 1120.32    35.5 1116.34    40.4 1114.38
    44.5 1113.33    50.3 1112.76    58.9 1112.31   102.1 1111.23   112.9 1111.59
   130.9  1111.5   151.1 1111.59   162.6  1111.8     166 1111.64   170.9 1110.16
   175.7 1109.62   179.81110.136   193.2 1111.73   204.7 1113.81   214.4 1114.87
   228.8 1115.37   262.7 1115.25   291.7 1115.79   309.5 1116.92   317.3 1117.83
#Mann= 4 ,-1,0
       0      .1       0     150     .05       0   170.9    .045       0
   179.8     .05       0
Bank Sta=170.9,179.8
XS Rating Curve= 0 ,0
Exp/Cntr(USF)=0,0
Exp/Cntr=0.3,0.1

Type RM Length L Ch R = 1 ,7784    ,122,122.6,118
XS GIS Cut Line= 2
2171783.94268043761051.6884235922171952.90934281761169.345837709
#Sta/Elev= 30
       0  1141.2     2.6 1138.99     4.1 1137.45     5.2 1136.17     9.6 1130.39
    12.7 1126.58    14.9 1124.23    19.8 1119.71    24.7  1115.7    27.1 1113.87
    29.5 1112.27    30.6 1111.76    34.4 1110.46    38.6 1109.74    44.2 1109.71
    51.6 1110.22    58.8 1110.25    73.4 1109.48    78.3 1109.03    83.1 1108.14
    84.6 1108.29    87.4 1109.14    90.3 1110.35    93.2 1111.16   102.6 1111.31
   135.6 1112.87   142.6 1113.08   167.9 1113.44   196.6 1113.04   205.9 1113.12
#Mann= 4 ,-1,0
       0      .1       0      60     .05       0    78.3    .045       0
    87.4     .05       0
Bank Sta=78.3,87.4
XS Rating Curve= 0 ,0
Exp/Cntr(USF)=0,0
Exp/Cntr=0.3,0.1

Type RM Length L Ch R = 1 ,7662    ,310,309,301.1
XS GIS Cut Line= 3
2171735.23336035761122.4566901982171737.09928154761155.755352657
2172015.88169285761313.590504421
#Sta/Elev= 30
       0 1125.88    14.7 1118.22    18.8  1116.4    22.8 1114.93    26.8 1113.88
    33.7 1113.31    44.4  1111.7    60.1 1110.14    63.1 1109.49      66 1108.54
    68.9 1107.76    71.9 1107.59    77.7 1107.85    80.1 1108.45    83.6 1109.72
      85 1110.06    87.4 1110.33    96.6 1110.15   110.4 1110.46   127.6 1110.34
     161 1111.54   203.9 1111.68   220.7 1111.99   262.1 1112.25   277.3 1112.79
   298.9 1112.83   312.5 1113.47   326.5 1114.51   344.8 1116.46   353.7 1117.95
#Mann= 5 ,-1,0
       0      .1       0      66    .045       0    80.1      .1       0
   93.35     .05       0  323.35     .06       0
Bank Sta=66,80.1
XS Rating Curve= 0 ,0
Exp/Cntr(USF)=0,0
Exp/Cntr=0.3,0.1

Type RM Length L Ch R = 1 ,7353    ,159.1,161.2,165.2
XS GIS Cut Line= 4
2171613.62187793761389.524617386 2171640.4308149761409.732059735
2171851.98378949761466.1310737282171921.41664404761510.510524592
#Sta/Elev= 30
       0 1130.33     8.2 1124.76      13 1121.95    18.7 1119.55    33.6    1114
    37.4 1112.38    41.6 1110.95    45.7 1109.89      54 1108.77    62.3 1108.41
    74.7 1108.59    85.2 1108.42    99.5 1108.51   108.1 1107.17     1181106.562
   124.4 1106.25   128.21106.746   132.7  1107.9   136.8 1108.46   153.4 1108.75
   186.5 1108.91   202.9 1109.55   215.5  1110.3   248.5 1110.84     267 1110.94
     286 1111.82   295.5 1112.72     305 1114.15   314.5 1116.45   334.9 1122.01
#Mann= 4 ,-1,0
       0      .1       0   93.57     .05       0     118    .045       0
   128.2     .05       0
Bank Sta=118,128.2
XS Rating Curve= 0 ,0
Exp/Cntr(USF)=0,0
Exp/Cntr=0.3,0.1

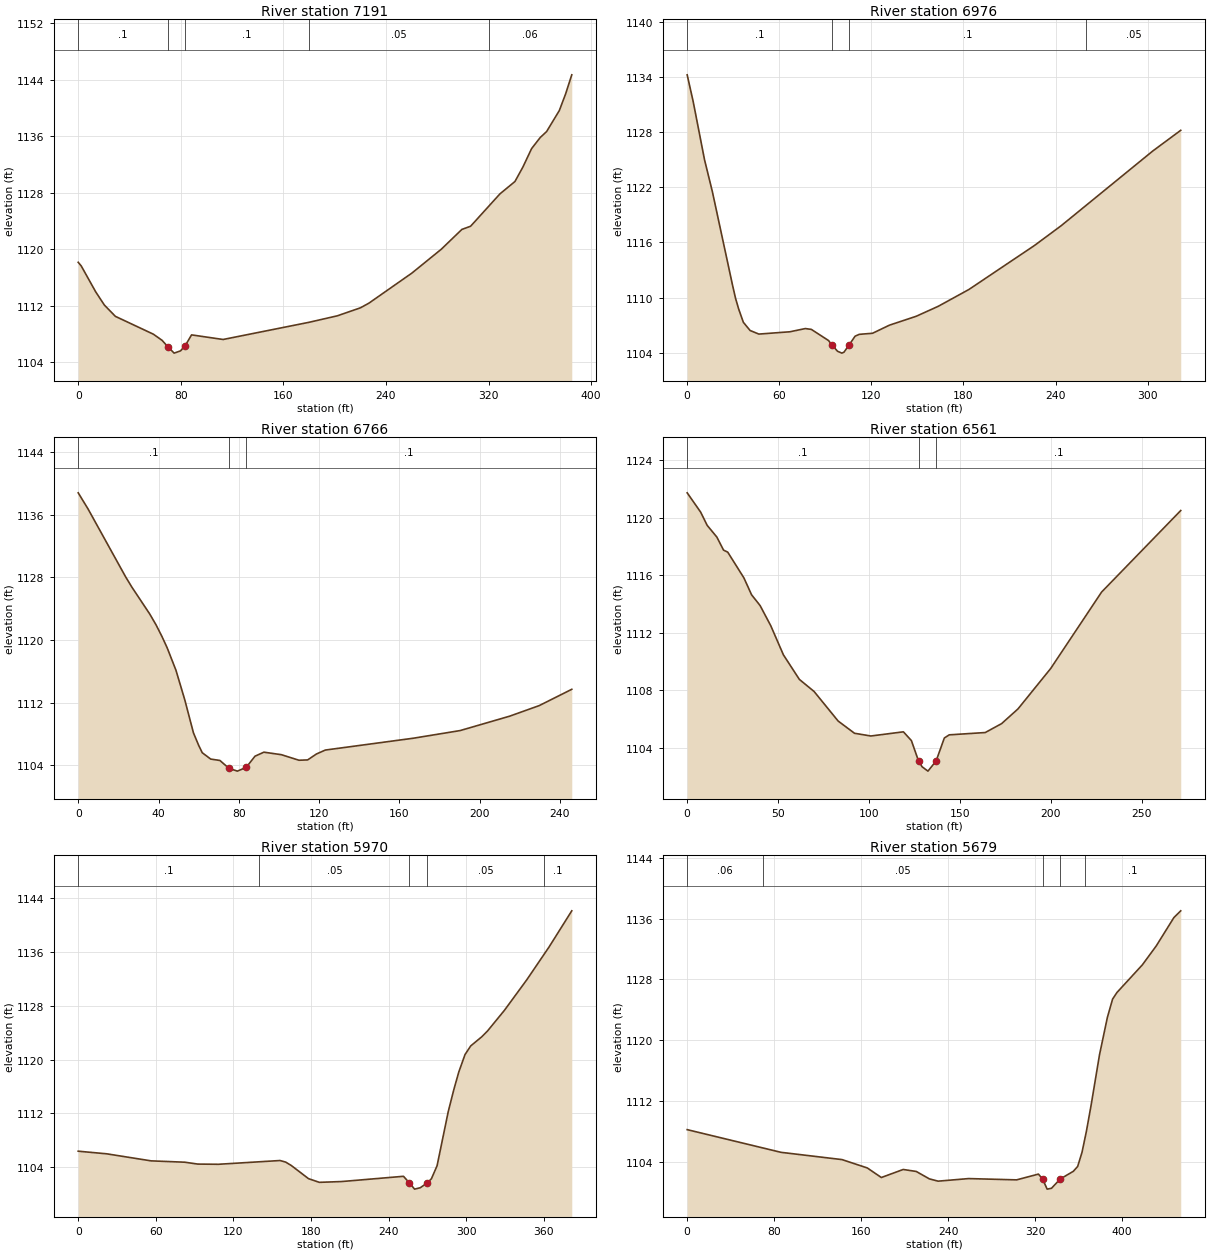
Type RM Length L Ch R = 1 ,7191    ,211.1,215.2,211.3
XS GIS Cut Line= 2
2171544.75127754 761485.193778722171856.03342087761711.580792051
#Sta/Elev= 30
       0 1118.15     2.4 1117.62    13.6 1113.98    20.4  1112.1      29  1110.5
    58.6 1107.98    65.4 1107.11      70 1106.18    74.8  1105.3    79.8 1105.62
    83.4 1106.35    88.4 1107.88     113 1107.23     180 1109.66   202.1 1110.58
   220.1 1111.71   226.8 1112.38   260.2 1116.62   283.1 1119.99   299.2  1122.8
     306 1123.25   328.9 1127.83   340.6 1129.58   346.8 1131.63   353.6 1134.24
   360.3  1135.8   365.3 1136.65   375.2 1139.62   380.1 1141.97   384.9 1144.67
#Mann= 5 ,-1,0
       0      .1       0      70    .045       0    83.4      .1       0
     180     .05       0     320     .06       0
Bank Sta=70,83.4
XS Rating Curve= 0 ,0
Exp/Cntr(USF)=0,0
Exp/Cntr=0.3,0.1

Type RM Length L Ch R = 1 ,6976    ,210.7,210.7,206
XS GIS Cut Line= 2
2171443.21004362761616.6979996992171697.89543362761813.122025971
#Sta/Elev= 30
       0 1134.21     3.9 1131.31    11.3 1124.98    16.4 1121.52    29.6 1111.31
    31.5 1109.93    33.5 1108.78    36.6 1107.31      41 1106.42    46.7 1106.03
    66.9 1106.28      77 1106.63    80.9 1106.54    92.1 1105.33    94.11104.897
      98 1104.16   100.8 1103.96   102.2 1104.07   105.6 1104.87   109.4  1105.8
   112.1    1106   120.8 1106.12   131.8    1107   149.3 1107.97   163.6 1109.05
   183.6 1110.88   226.3 1115.66   243.7 1117.81   303.3 1125.92   321.6 1128.18
#Mann= 4 ,-1,0
       0      .1       0    94.1    .045       0   105.6      .1       0
     260     .05       0
Bank Sta=94.1,105.6
XS Rating Curve= 0 ,0
Exp/Cntr(USF)=0,0
Exp/Cntr=0.3,0.1

Type RM Length L Ch R = 1 ,6766    ,203.3,204.3,204.5
XS GIS Cut Line= 2
2171331.68114735761766.5129349912171556.40355029761866.389558519
#Sta/Elev= 30
       0 1138.79     4.9 1136.73    23.6 1128.07    26.8 1126.72    35.6 1123.33
    38.8 1121.92    41.8  1120.4    44.3 1119.01    48.7 1116.13    53.1 1112.35
    57.4 1108.15      60 1106.55    61.8  1105.6      66 1104.79    70.6 1104.61
    75.1 1103.61    79.3 1103.25    83.7 1103.73    88.1 1105.16    92.5 1105.67
   101.2 1105.35     110 1104.64   114.3 1104.68   118.7 1105.44   123.1 1105.94
   166.9 1107.45   190.3 1108.43     215 1110.27   229.7 1111.62   245.9  1113.7
#Mann= 3 ,-1,0
       0      .1       0    75.1    .045       0    83.7      .1       0
Bank Sta=75.1,83.7
XS Rating Curve= 0 ,0
Exp/Cntr(USF)=0,0
Exp/Cntr=0.3,0.1

Type RM Length L Ch R = 1 ,6561    ,587.4,591.6,585.3
XS GIS Cut Line= 2
2171234.38887142 761928.993431792171475.74073217762053.040198212
#Sta/Elev= 30
       0 1121.72     7.4 1120.38      11 1119.46    16.3 1118.65      20 1117.74
    22.3  1117.6    31.2 1115.81    35.4 1114.64    40.1 1113.89      46 1112.48
    52.9 1110.47    61.7 1108.76    69.8 1107.92      83 1105.87      92 1105.02
     101 1104.83   118.9 1105.12   123.3 1104.51   127.31103.068   129.2 1102.69
   132.4 1102.39   136.9  1103.1   141.4 1104.69   144.1 1104.91   163.9 1105.07
   172.9 1105.69   181.9 1106.71   199.9 1109.52   227.9 1114.83   271.4 1120.49
#Mann= 3 ,-1,0
       0      .1       0   127.3    .045       0   136.9      .1       0
Bank Sta=127.3,136.9
XS Rating Curve= 0 ,0
Exp/Cntr(USF)=0,0
Exp/Cntr=0.3,0.1

Type RM Length L Ch R = 1 ,5970    ,291.5,290.5,282.3
XS GIS Cut Line= 2
  2171064.180998762212.3466309472171416.24609593762359.165267533
#Sta/Elev= 30
       0 1106.36      22 1105.97    56.3 1104.92    82.3 1104.72    92.4 1104.44
   108.3 1104.41     156 1104.97   160.3 1104.74   164.7 1104.23     178 1102.27
   186.4 1101.72   203.7 1101.84   251.4 1102.62     256 1101.64     260 1100.71
   264.4 1100.92   269.8 1101.63     273 1102.25   277.4  1104.2     286 1112.24
   290.4 1115.58   294.2 1118.17     299 1120.76   303.4 1122.04     312 1123.41
   316.4 1124.27   329.4 1127.33   346.7 1131.88     364 1136.79   381.5 1142.16
#Mann= 5 ,-1,0
       0      .1       0     140     .05       0     256    .045       0
   269.8     .05       0     360      .1       0
Bank Sta=256,269.8
XS Rating Curve= 0 ,0
Exp/Cntr(USF)=0,0
Exp/Cntr=0.3,0.1

Type RM Length L Ch R = 1 ,5679    ,328.7,332,328.1
XS GIS Cut Line= 4
2170934.14163417762542.8383782052171010.05500554762549.152946778
2171359.16660558762577.1459983862171386.43292381762572.651550327
#Sta/Elev= 30
       0  1108.2    86.3 1105.21   142.5 1104.25   165.7 1103.15   178.6 1101.89
   198.7 1102.95   210.7 1102.69   222.8 1101.71   230.8 1101.41   258.9 1101.75
     303 1101.58   323.1 1102.34   327.1 1101.66   327.1 1101.65   331.1 1100.36
   335.1 1100.47   343.1 1101.69   355.2 1102.71   359.2 1103.35   363.2 1105.22
   367.2 1107.96   371.7 1111.54   379.3 1118.08   386.5 1122.98   391.3  1125.4
   395.3 1126.27   418.7 1129.92   431.5 1132.42   447.7 1136.15     454 1137.04
#Mann= 5 ,-1,0
       0     .06       0      70     .05       0   327.1    .045       0
   343.1     .05       0  366.18      .1       0
Bank Sta=327.1,343.1
XS Rating Curve= 0 ,0
Exp/Cntr(USF)=0,0
Exp/Cntr=0.3,0.1

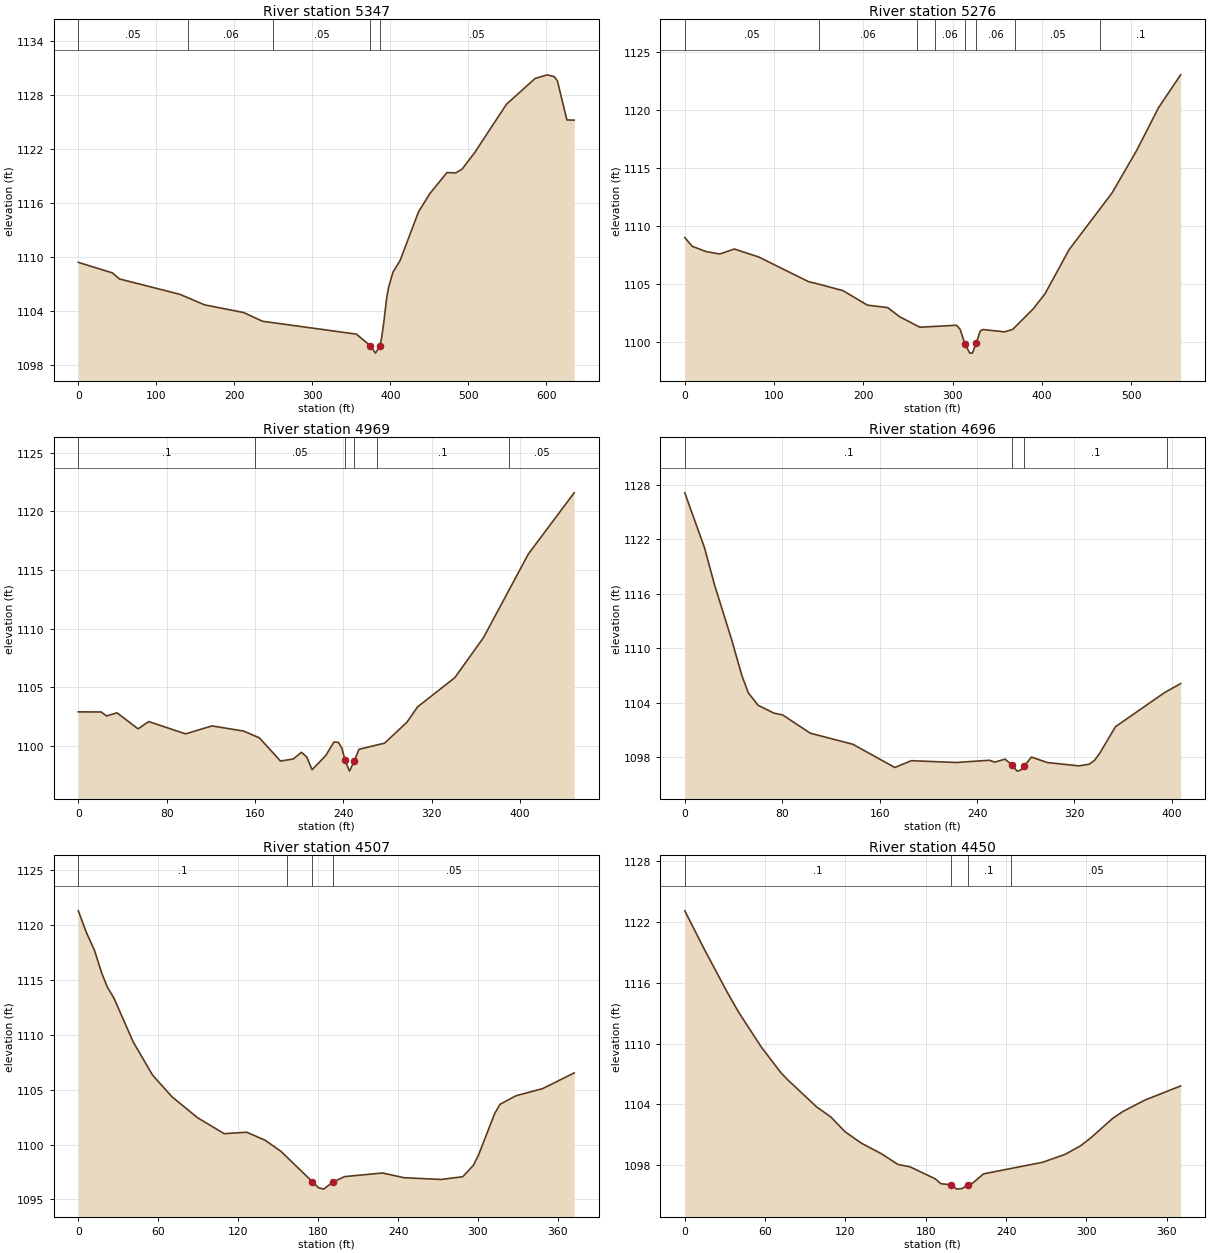
Type RM Length L Ch R = 1 ,5347    ,66.2,70.8,68.8
XS GIS Cut Line= 3
  2170881.553939762568.3575352392171296.68382555762794.276243997
2171327.35339798762954.372251693
#Sta/Elev= 30
       0 1109.37    43.6  1108.2    52.7 1107.53   130.5 1105.81   161.8 1104.65
   211.9  1103.8     236 1102.83   356.4  1101.4   374.2 1100.12     381 1099.29
   386.6 1100.08   388.9 1101.06   391.8 1102.85     395 1105.26   397.7 1106.59
   403.4 1108.29   412.5 1109.58     436 1114.96   450.8 1117.03   472.6 1119.34
   483.7  1119.3   491.9 1119.71   508.2 1121.57   548.9 1126.93   585.5 1129.78
   601.1 1130.19     610 1129.99   614.1 1129.53   626.3 1125.18   635.6 1125.16
#Mann= 5 ,-1,0
       0     .05       0     140     .06       0     250     .05       0
   374.2    .045       0   386.6     .05       0
Bank Sta=374.2,386.6
XS Rating Curve= 0 ,0
Exp/Cntr(USF)=0,0
Exp/Cntr=0.3,0.1

Type RM Length L Ch R = 1 ,5276    ,303.8,307.5,306.1
XS GIS Cut Line= 4
2170871.10751615762626.9329857242171256.39578296762829.864188491
2171275.74290812762885.0393232172171289.99662513762945.003300435
#Sta/Elev= 30
       0    1109     8.4 1108.25    23.8  1107.8    39.2 1107.59    55.5 1108.02
    82.6 1107.34   138.7 1105.21     150    1105   177.2 1104.44   204.6 1103.19
   227.3 1102.98   240.8 1102.19   263.4 1101.29   304.5 1101.46   308.6  1101.1
   313.8 1099.86   319.3 1099.06   322.3 1099.06   326.7 1099.97   331.1 1100.97
   334.1 1101.09   358.4 1100.89   367.4  1101.1   390.4 1102.87   403.6 1104.16
   430.7 1107.97   478.7 1112.84   506.4 1116.51   530.9 1120.19   555.6 1123.01
#Mann= 8 ,-1,0
       0     .05       0     150     .06       0     260     .05       0
     280     .06       0   313.8    .045       0   326.7     .06       0
     370     .05       0  465.46      .1       0
Bank Sta=313.8,326.7
XS Rating Curve= 0 ,0
Exp/Cntr(USF)=0,0
Exp/Cntr=0.3,0.1

Type RM Length L Ch R = 1 ,4969    ,271.8,272.8,269.1
XS GIS Cut Line= 2
2170874.80764172 762899.076337392171251.00959035763143.774065034
#Sta/Elev= 30
       0 1102.89    20.7 1102.88    25.6 1102.54      35 1102.81    54.1 1101.44
    63.7 1102.06    97.1 1101.01   120.9 1101.69   149.6 1101.25   163.9 1100.67
     183 1098.69   194.6 1098.87     202 1099.44   206.8 1099.03   211.6 1097.95
   223.9 1099.15   231.3 1100.31   235.4 1100.29   238.6 1099.78   241.51098.746
   245.4 1097.83   249.8 1098.69     254 1099.69   277.2 1100.22   297.5 1102.01
     307 1103.31   340.8 1105.81   366.8 1109.24   407.3 1116.36   448.8 1121.59
#Mann= 6 ,-1,0
       0      .1       0     160     .05       0   241.5    .045       0
   249.8     .05       0     270      .1       0     390     .05       0
Bank Sta=241.5,249.8
XS Rating Curve= 0 ,0
Exp/Cntr(USF)=0,0
Exp/Cntr=0.3,0.1

Type RM Length L Ch R = 1 ,4696    ,190.5,189.2,184.3
XS GIS Cut Line= 3
2170741.42409938763162.7118029432170810.45016235763131.434368161
2171117.83184901763255.465575058
#Sta/Elev= 30
       0  1127.1    16.2 1121.05    24.4 1116.97    38.2 1111.05    46.9 1106.96
    52.2 1105.07    60.1 1103.71    73.3 1102.83    80.4 1102.64     103 1100.63
     138 1099.41   172.5 1096.85     186  1097.6   222.9  1097.4   250.2 1097.65
   254.5 1097.44   263.1 1097.77     269 1097.08   272.9 1096.45   276.1 1096.58
   278.91097.041   284.7    1098   297.6  1097.4   323.5 1097.03   332.1 1097.21
   336.4 1097.62   340.8 1098.43   353.7 1101.34   393.9 1105.09   407.2 1106.09
#Mann= 4 ,-1,0
       0      .1       0     269    .045       0   278.9      .1       0
  395.78     .05       0
Bank Sta=269,278.9
XS Rating Curve= 0 ,0
Exp/Cntr(USF)=0,0
Exp/Cntr=0.3,0.1

Type RM Length L Ch R = 1 ,4507    ,53.6,56.7,49.7
XS GIS Cut Line= 3
2170774.22504393 763383.549384472170878.28455733 763311.77426634
2171123.90121955 763301.53587254
#Sta/Elev= 30
       0 1121.28       6 1119.32    12.1 1117.69    17.5 1115.63    21.8 1114.33
    26.7 1113.34    41.2 1109.34    55.8 1106.31    70.4 1104.34    89.4 1102.45
   109.5 1100.99   126.4 1101.12   140.3 1100.39   152.3 1099.36   175.61096.623
   180.3 1096.07   184.2 1095.94     1911096.578   199.9 1097.08   228.4 1097.41
   244.4 1096.98   272.4 1096.82   288.6 1097.07   296.5  1098.1   300.5 1099.07
   312.5 1102.81   316.5 1103.66   328.5 1104.44   348.5 1105.09   372.2 1106.52
#Mann= 4 ,-1,0
       0      .1       0  156.41     .05       0   175.6    .045       0
     191     .05       0
Bank Sta=175.6,191
XS Rating Curve= 0 ,0
Exp/Cntr(USF)=0,0
Exp/Cntr=0.3,0.1

Type RM Length L Ch R = 1 ,4450    ,171,174.3,174.3
XS GIS Cut Line= 3
2170794.16065802 763440.083300492170894.47862527763352.101204359
2171131.15764211763340.198091306
#Sta/Elev= 30
       0 1123.11    14.8 1119.26    31.8 1115.05    40.3 1113.08    57.3 1109.63
    71.8 1107.12    77.2 1106.38    98.4 1103.75   109.1 1102.75   119.7 1101.29
   131.8 1100.17   147.1  1099.1   159.2 1098.06   168.3 1097.82   187.2 1096.63
   191.2 1096.16   199.2 1096.04   203.2 1095.62   207.2 1095.68   211.2 1096.02
   215.2 1096.23   223.2 1097.13   267.3 1098.27     284 1099.05   295.3 1099.87
   303.3 1100.68   319.4 1102.58   327.4  1103.3   343.8 1104.42   370.4 1105.81
#Mann= 4 ,-1,0
       0      .1       0   199.2    .045       0   211.2      .1       0
  243.43     .05       0
Bank Sta=199.2,211.2
XS Rating Curve= 0 ,0
Exp/Cntr(USF)=0,0
Exp/Cntr=0.3,0.1

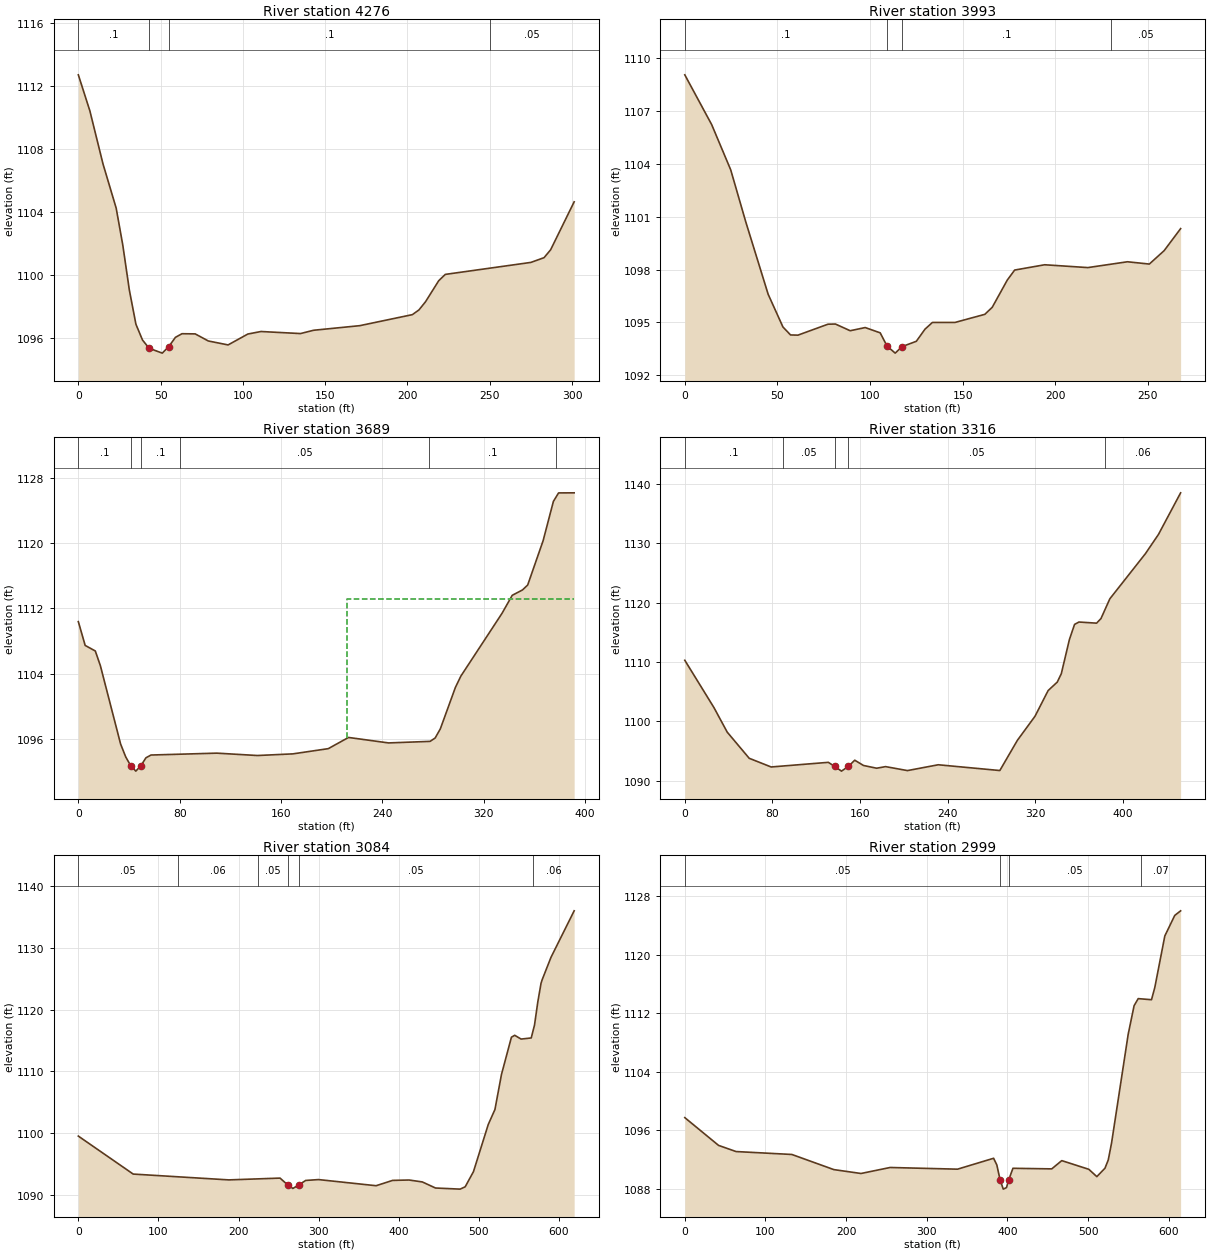
Type RM Length L Ch R = 1 ,4276    ,278.4,282.2,279.5
XS GIS Cut Line= 2
2170853.16770663763504.994520127 2171154.4621876763503.329909735
#Sta/Elev= 30
       0 1112.71       7 1110.43      15 1107.06      23 1104.26      27 1101.93
      31 1099.07      35  1096.9      39  1095.9      43 1095.38      51 1095.07
      55 1095.49      59 1096.07      63  1096.3      71 1096.29      79 1095.84
      91 1095.59     103 1096.28     111 1096.44     135 1096.31     143 1096.52
     171 1096.81     203 1097.51     207 1097.81     211 1098.33     219 1099.66
     223 1100.06     275 1100.82     283 1101.12     287 1101.62   301.3 1104.66
#Mann= 4 ,-1,0
       0      .1       0      43    .045       0      55      .1       0
     250     .05       0
Bank Sta=43,55
XS Rating Curve= 0 ,0
Exp/Cntr(USF)=0,0
Exp/Cntr=0.3,0.1

Type RM Length L Ch R = 1 ,3993    ,305.9,304.6,303.2
XS GIS Cut Line= 2
 2170879.5854631763725.4678822832171144.94919227763760.635788249
#Sta/Elev= 30
       0 1109.04    14.5 1106.22    24.8 1103.65    32.9 1100.71      45  1096.6
      53 1094.74    57.1 1094.29    61.1 1094.28    77.3  1094.9    81.3 1094.91
    89.3 1094.53    97.4 1094.71   105.5 1094.41   109.21093.661   113.6 1093.26
   117.3 1093.63     125 1093.93   129.7 1094.62   133.7    1095   145.9    1095
     162 1095.46     166 1095.86   174.1  1097.4   178.1 1097.97   194.3 1098.27
   217.6 1098.11     239 1098.44   250.8 1098.31   258.8 1099.07   267.7 1100.32
#Mann= 4 ,-1,0
       0      .1       0   109.2    .045       0   117.3      .1       0
     230     .05       0
Bank Sta=109.2,117.3
XS Rating Curve= 0 ,0
Exp/Cntr(USF)=0,0
Exp/Cntr=0.3,0.1

Type RM Length L Ch R = 1 ,3689    ,369.4,373.1,370
XS GIS Cut Line= 3
2170822.79345919764010.4565678522171080.05566607764004.389062973
2171212.32727244763981.332544432
#Sta/Elev= 30
       0 1110.38     5.4 1107.47    13.4 1106.79    17.4    1105    33.4  1095.4
    37.4 1093.84    41.4 1092.74    45.4 1092.09    49.4 1092.75    53.4 1093.72
    57.4 1094.06   109.4 1094.29   141.4    1094   169.4  1094.2   197.4 1094.84
   213.4 1096.21     245 1095.54   277.8 1095.73   281.8 1096.14   285.9 1097.26
   297.8 1102.33   302.1 1103.71   334.6 1111.39   342.7  1113.6   350.8 1114.26
   354.9 1114.86   367.1 1120.29   375.2 1125.09   379.3 1126.13   391.6 1126.14
#Mann= 6 ,-1,0
       0      .1       0    41.4    .045       0    49.4      .1       0
      80     .05       0  277.33      .1       0  377.33     .06       0
#XS Ineff= 2 , 0
                          212.51         1113.14
Permanent Ineff=
       F       F
Bank Sta=41.4,49.4
XS Rating Curve= 0 ,0
Exp/Cntr(USF)=0,0
Exp/Cntr=0.3,0.1

Type RM Length L Ch R = 1 ,3316    ,251.5,231.4,216.9
XS GIS Cut Line= 3
2170821.57995822764319.8993166982171194.12475781764290.775293277
2171271.78882026764277.426782543
#Sta/Elev= 30
       0 1110.28    26.7 1102.28    38.7 1098.18    58.8 1093.77    78.8 1092.31
     131 1093.09   136.71092.411     143 1091.61   149.21092.397   155.1 1093.45
   163.1 1092.56   175.1  1092.1   183.2 1092.37   203.2  1091.7   231.3 1092.68
   287.5 1091.71   303.5 1096.79   319.6 1100.85   331.6 1105.18   339.9  1106.6
   343.6 1108.01     351 1113.77   355.7 1116.32   359.7 1116.72   375.8 1116.53
   379.8  1117.3   387.9 1120.63   420.4 1128.24   432.3 1131.48   452.5 1138.48
#Mann= 5 ,-1,0
       0      .1       0      90     .05       0   136.7    .045       0
   149.2     .05       0  383.68     .06       0
Bank Sta=136.7,149.2
XS Rating Curve= 0 ,0
Exp/Cntr(USF)=0,0
Exp/Cntr=0.3,0.1

Type RM Length L Ch R = 1 ,3084    ,87,85.4,85
XS GIS Cut Line= 4
2170916.75970208 764680.254318872171013.13892799764640.847061029
2171012.49402382764377.0812546322171256.26780088764317.105166625
#Sta/Elev= 30
       0 1099.57    68.5 1093.44   187.8  1092.5   251.8 1092.79   261.31091.696
   267.8 1091.12   275.2 1091.69   283.8 1092.41   299.8 1092.55   371.7 1091.56
   392.3 1092.42   412.9 1092.48   429.4 1092.17   445.8 1091.19   476.6 1091.01
   482.9 1091.39   493.2 1093.83   511.7 1101.45     520 1103.85   528.2 1109.53
   540.6 1115.53   544.7 1115.84   552.7 1115.23   565.3 1115.41   569.4 1117.48
   573.5  1121.2   577.6 1124.26   579.1 1124.85     590 1128.43   618.9 1135.93
#Mann= 6 ,-1,0
       0     .05       0  124.12     .06       0  224.12     .05       0
   261.3    .045       0   275.2     .05       0  567.89     .06       0
Bank Sta=261.3,275.2
XS Rating Curve= 0 ,0
Exp/Cntr(USF)=0,0
Exp/Cntr=0.3,0.1

Type RM Length L Ch R = 1 ,2999    ,237.4,252.6,268.9
XS GIS Cut Line= 5
 2170931.8810023764715.0110408222170966.25668928764724.052416714
2171109.87455381764664.7085153972171092.46214116   764400.942709
2171247.23914247764362.248458673
#Sta/Elev= 30
       0 1097.73    41.9 1093.93    63.6 1093.09   132.8 1092.69   184.8 1090.62
   218.5 1090.09   254.6 1090.91   338.2 1090.68   382.9 1092.17   386.9 1091.26
   390.9 1089.25   394.9 1087.95   398.9 1088.16   401.51089.179   406.9  1090.8
     455 1090.72   467.4 1091.85     501 1090.66   510.9 1089.66     521 1090.81
   525.1 1091.95   529.2 1094.28   549.8 1109.14   557.1 1113.04   562.2 1114.01
   578.7 1113.86   582.8 1115.54   595.2 1122.58   607.5 1125.39   614.8 1126.02
#Mann= 4 ,-1,0
       0     .05       0   390.9    .045       0   401.5     .05       0
  565.28     .07       0
Bank Sta=390.9,401.5
XS Rating Curve= 0 ,0
Exp/Cntr(USF)=0,0
Exp/Cntr=0.3,0.1

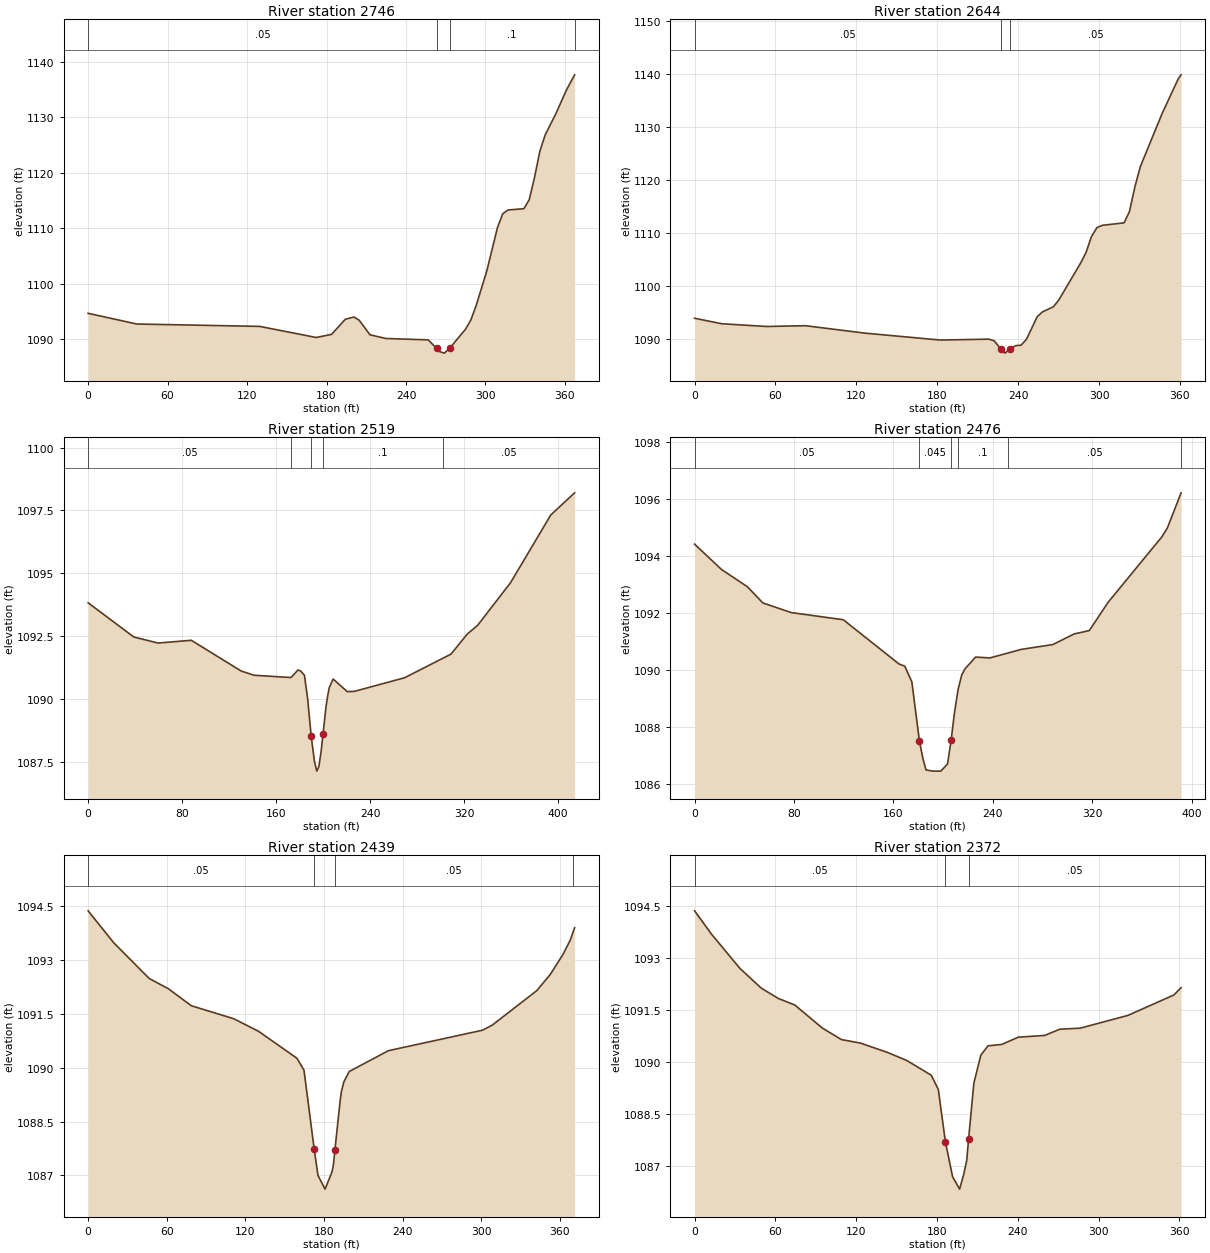
Type RM Length L Ch R = 1 ,2746    ,101.9,102.5,103
XS GIS Cut Line= 4
2170956.60767098764738.261447464 2171006.1211049764750.578146354
2171131.19069531764670.2181699412171298.31890214764657.574329021
#Sta/Elev= 30
       0 1094.68    36.7 1092.75   129.5 1092.32   172.2 1090.32   183.8 1090.88
   194.2 1093.61   200.7 1094.01   204.7 1093.42   212.8 1090.81   224.7 1090.14
   256.8 1089.89   263.11088.359   264.9 1087.81   268.9  1087.5   272.9 1088.35
   284.9 1091.81   288.9 1093.44   292.9 1096.03     301 1102.32     309 1110.09
     313 1112.61     317 1113.31     329 1113.54     333 1115.14   337.1 1119.26
   341.1 1123.94   345.1 1126.86   353.1 1130.65   361.1 1134.93   367.3 1137.68
#Mann= 4 ,-1,0
       0     .05       0   263.1    .045       0   272.9      .1       0
  367.29     .06       0
Bank Sta=263.1,272.9
XS Rating Curve= 0 ,0
Exp/Cntr(USF)=0,0
Exp/Cntr=0.3,0.1

Type RM Length L Ch R = 1 ,2644    ,117.7,125,131.9
XS GIS Cut Line= 4
2170964.97233437764749.8379107242171030.40693739 764769.76914038
2171224.46677135764766.9744872532171322.11902117764754.944862276
#Sta/Elev= 30
       0 1093.84    20.1  1092.8    53.5 1092.28    82.2 1092.43   126.2 1091.03
   182.2 1089.72   218.2 1089.89   222.2 1089.59   227.21088.022   230.2 1087.25
   234.2 1088.06   238.2 1088.66   242.2 1088.75   246.2 1089.86   254.2 1094.15
   258.2 1095.06   266.2 1096.01   270.2 1097.29   286.4 1104.27   290.4 1106.26
   294.4 1109.26   298.5 1110.96   302.5 1111.39   318.6 1111.85   322.6 1113.98
   326.7 1118.73   330.7 1122.49   346.8 1132.48   358.9 1139.11   360.9 1139.81
#Mann= 3 ,-1,0
       0     .05       0   227.2    .045       0   234.2     .05       0
Bank Sta=227.2,234.2
XS Rating Curve= 0 ,0
Exp/Cntr(USF)=0,0
Exp/Cntr=0.3,0.1

Type RM Length L Ch R = 1 ,2519    ,44.1,43.5,44.6
XS GIS Cut Line= 4
2170958.47330548764757.1831199662171028.52663271764775.033993497
2171253.19136821764973.4687632652171282.70887193 765003.28320576
#Sta/Elev= 30
       0 1093.83    38.9 1092.47    59.5 1092.23    87.8 1092.34   130.2 1091.12
   141.2 1090.95   172.7 1090.86   178.6 1091.16   180.9 1091.12   184.1 1090.95
   186.9 1089.98   189.8 1088.54   192.6 1087.53   194.6 1087.14   196.4 1087.33
   198.3 1087.93   199.91088.617   202.4 1089.69   203.9 1090.14   205.2 1090.46
   208.5  1090.8   220.5  1090.3   226.6 1090.31   269.3 1090.85   308.8 1091.79
   322.7 1092.59   331.4 1092.93   359.5 1094.63   393.7 1097.32     414  1098.2
#Mann= 5 ,-1,0
       0     .05       0  172.29      .1       0   189.8    .045       0
   199.9      .1       0  302.29     .05       0
Bank Sta=189.8,199.9
XS Rating Curve= 0 ,0
Exp/Cntr(USF)=0,0
Exp/Cntr=0.3,0.1

Type RM Length L Ch R = 1 ,2476    ,37.3,36.5,36.2
XS GIS Cut Line= 3
2170935.29124327764777.7075561742170995.05720932764794.213101279
2171230.16676874765024.866753528
#Sta/Elev= 30
       0  1094.4    21.7 1093.51    42.4 1092.91    54.9 1092.34    77.7    1092
   119.6 1091.75   164.4  1090.2   169.1 1090.12   174.8 1089.57   180.9 1087.49
   183.7 1086.88   186.2 1086.48   191.9 1086.44   198.1 1086.44   203.5 1086.69
   206.41087.525   209.1 1088.49     212  1089.3   214.9 1089.81   217.6 1090.03
   226.1 1090.44   237.6 1090.41   262.9 1090.71   288.3 1090.88   305.3 1091.25
   317.6 1091.37   332.5 1092.35     376 1094.66   380.4 1094.97   391.4  1096.2
#Mann= 6 ,-1,0
       0     .05       0   180.9    .045       0   206.4     .05       0
     212      .1       0     252     .05       0  391.36      .1       0
Bank Sta=180.9,206.4
XS Rating Curve= 0 ,0
Exp/Cntr(USF)=0,0
Exp/Cntr=0.3,0.1

Type RM Length L Ch R = 1 ,2439    ,65.8,66.8,68.6
XS GIS Cut Line= 2
2170929.48058065764792.1774033522171206.07281447765040.107229523
#Sta/Elev= 27
       0 1094.36    19.6 1093.47    46.6 1092.48    61.4 1092.19    78.8 1091.72
   111.1 1091.36   130.1 1091.01   159.4 1090.26   164.8 1089.93   172.6 1087.73
   175.5    1087   180.9 1086.62   186.3 1087.11   187.3 1087.31   188.41087.707
   192.4 1089.08   193.3 1089.32   195.2  1089.6   199.3 1089.89   229.2 1090.47
   301.1 1091.04   308.5 1091.18   342.5 1092.14   352.8 1092.59   362.4 1093.14
     368 1093.54   371.4 1093.89
#Mann= 4 ,-1,0
       0     .05       0   172.6    .045       0   188.4     .05       0
     370      .1       0
Bank Sta=172.6,188.4
XS Rating Curve= 0 ,0
Exp/Cntr(USF)=0,0
Exp/Cntr=0.3,0.1

Type RM Length L Ch R = 1 ,2372    ,158.4,148.7,139.2
XS GIS Cut Line= 2
2170898.66849242 764848.785658462171173.11104567765083.817401188
#Sta/Elev= 30
       0 1094.36    12.5 1093.69    33.6  1092.7    49.4 1092.13    62.1 1091.83
    74.4 1091.64      95 1090.97   109.1 1090.64   123.1 1090.54   143.2 1090.27
   157.4 1090.04   175.8 1089.61     181  1089.2   186.3 1087.68   191.6 1086.68
   196.8 1086.32   199.9 1086.75   202.1 1087.15   203.5 1087.77   207.4 1089.38
   212.6 1090.19   217.9 1090.46   228.1  1090.5   240.4 1090.71     260 1090.76
   271.2 1090.94   286.4 1090.97   321.9 1091.34     356 1091.93   361.3 1092.14
#Mann= 3 ,-1,0
       0     .05       0   186.3    .045       0   203.5     .05       0
Bank Sta=186.3,203.5
XS Rating Curve= 0 ,0
Exp/Cntr(USF)=0,0
Exp/Cntr=0.3,0.1