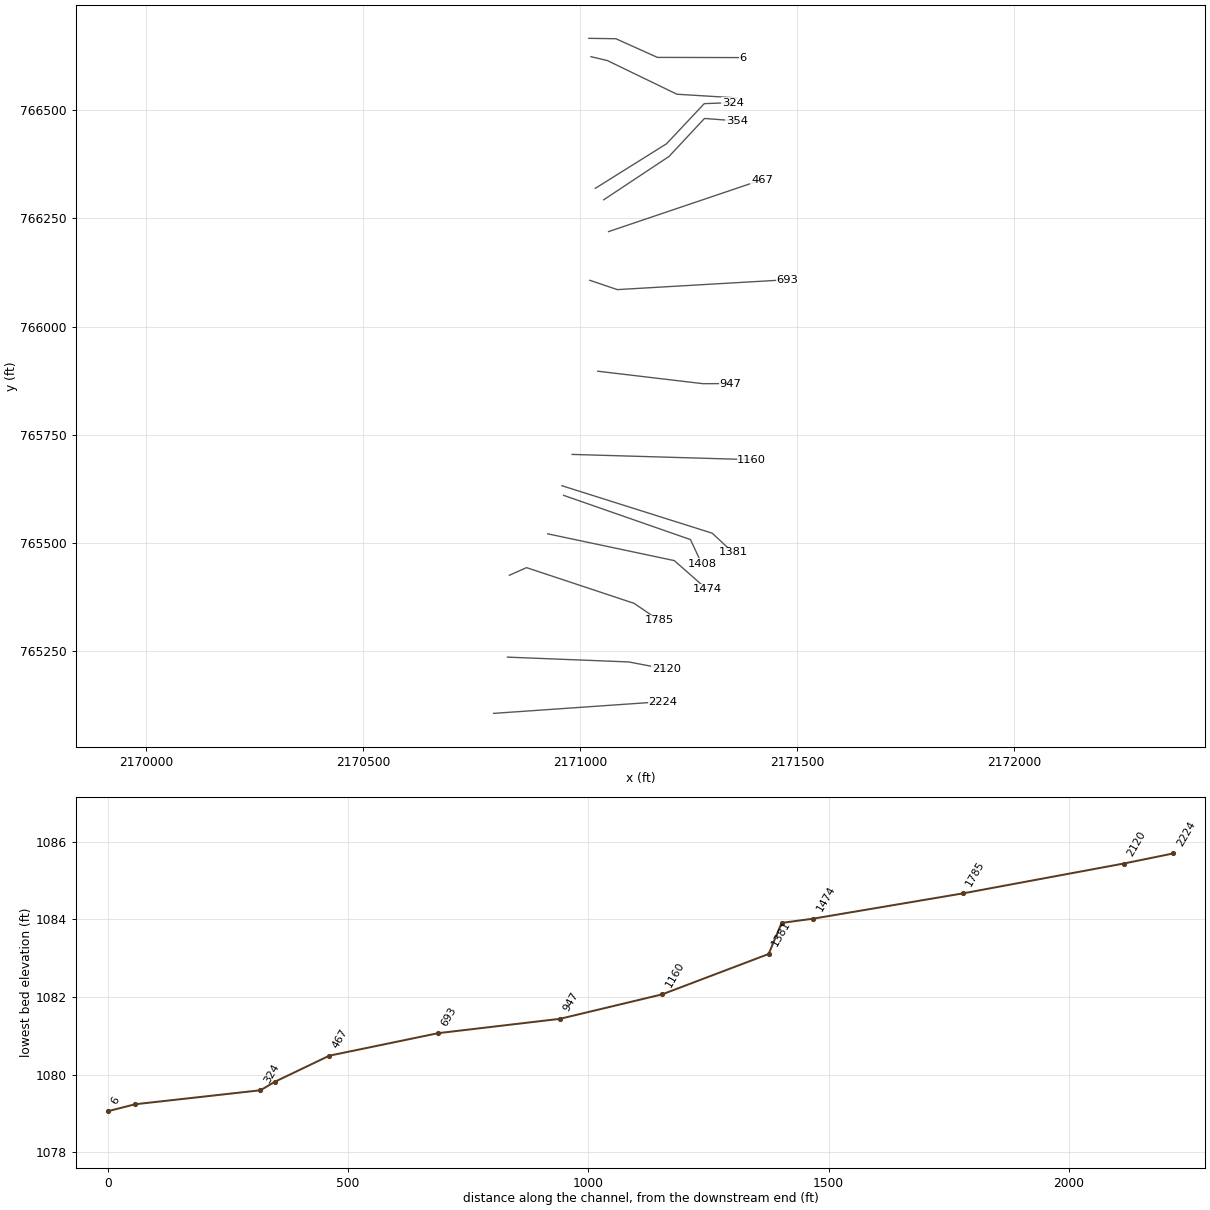
HEC-RAS study ROOTINGCK.prj: ROOTINGCK

--- ROOTINGCK.g01 (geometry) --- (continued)

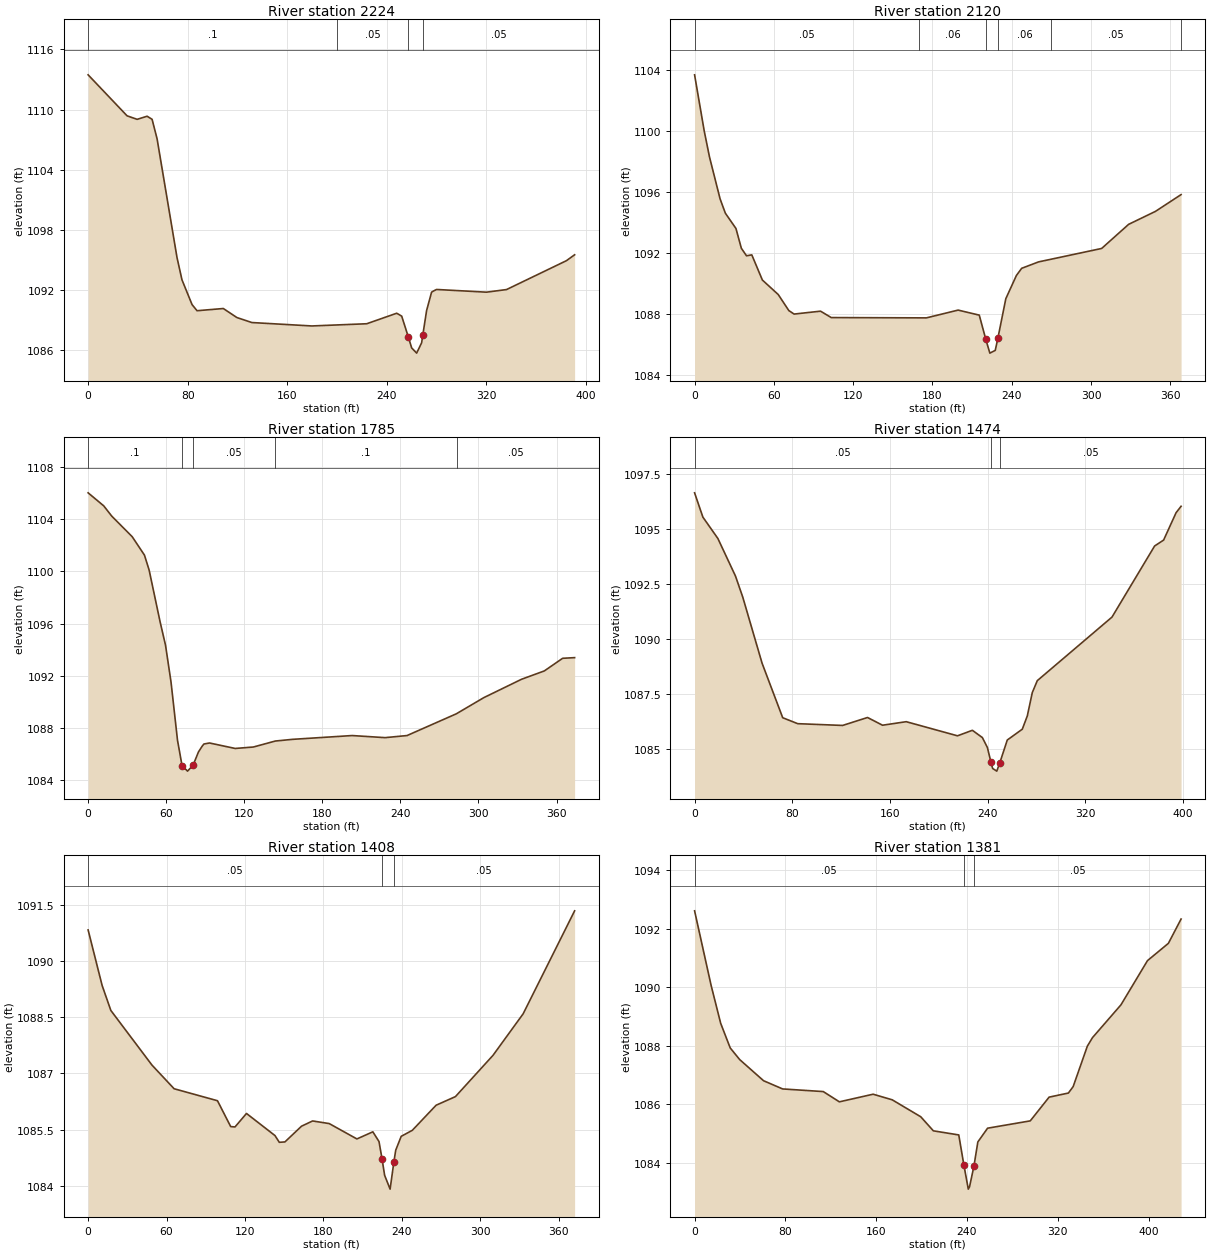
Type RM Length L Ch R = 1 ,2224    ,104.4,103.1,101.9
XS GIS Cut Line= 2
2170800.91788507765104.547619045 2171190.7266291765131.776906313
#Sta/Elev= 30
       0 1113.46    31.3 1109.37    39.4 1109.02    47.4 1109.33    51.4 1109.02
    55.4 1107.08    71.4 1095.24    75.4 1093.01    83.5 1090.54    87.5 1089.93
   108.6 1090.15   119.5 1089.25   131.6 1088.75   179.7 1088.41   223.8 1088.63
   247.9 1089.68   251.9 1089.39   257.2 1087.32   259.9 1086.22   263.9  1085.7
   267.9 1086.73   268.8 1087.46   271.9 1089.95   275.9 1091.78   277.2 1091.88
   279.9 1092.05     320 1091.78   336.1 1092.04   384.2 1094.92   390.8 1095.51
#Mann= 4 ,-1,0
       0      .1       0     200     .05       0   257.2    .045       0
   268.8     .05       0
Bank Sta=257.2,268.8
XS Rating Curve= 0 ,0
Exp/Cntr(USF)=0,0
Exp/Cntr=0.3,0.1

Type RM Length L Ch R = 1 ,2120    ,333,335.2,333
XS GIS Cut Line= 3
2170832.90316686765234.7274530472171112.26151171765223.602858865
2171199.19405449765206.916259193
#Sta/Elev= 30
       0 1103.68     7.3    1100    11.3 1098.29    19.3 1095.55    23.3 1094.61
    31.3 1093.61    35.4 1092.31    39.3 1091.82    43.3 1091.88    51.3 1090.23
    63.3 1089.28    71.3 1088.23    75.3    1088    95.3 1088.19   103.4 1087.77
   175.4 1087.75   199.4 1088.26   215.4 1087.93   220.2 1086.39   223.4 1085.44
   227.5 1085.62   229.51086.425   235.5 1089.01   243.5 1090.53   247.5    1091
   260.3 1091.42     308  1092.3   328.4 1093.88   348.7 1094.73   368.1 1095.83
#Mann= 6 ,-1,0
       0     .05       0     170     .06       0   220.2    .045       0
   229.5     .06       0     270     .05       0   368.1      .1       0
Bank Sta=220.2,229.5
XS Rating Curve= 0 ,0
Exp/Cntr(USF)=0,0
Exp/Cntr=0.3,0.1

Type RM Length L Ch R = 1 ,1785    ,304.1,311,309
XS GIS Cut Line= 4
2170837.25884725765424.2121794572170876.82018616765441.905023686
2171124.73964595765359.1622836212171181.78700988765319.954254426
#Sta/Elev= 30
       0 1106.03      12 1105.03    18.1 1104.25    33.9 1102.66    43.3 1101.25
    46.9  1100.1    55.3 1096.14    59.5 1094.33    63.7 1091.52    68.7 1087.04
    72.2 1085.09    76.4 1084.67    80.6 1085.11    84.8 1086.14    87.7 1086.59
      89 1086.75    93.3 1086.83     113 1086.41     127 1086.52   143.9 1086.98
   157.2 1087.11   202.9  1087.4   228.2 1087.24   245.1  1087.4     283 1089.07
   304.1 1090.31   333.1 1091.72   350.6 1092.36   364.7 1093.33   373.9 1093.38
#Mann= 5 ,-1,0
       0      .1       0    72.2    .045       0    80.6     .05       0
  143.34      .1       0  283.34     .05       0
Bank Sta=72.2,80.6
XS Rating Curve= 0 ,0
Exp/Cntr(USF)=0,0
Exp/Cntr=0.3,0.1

Type RM Length L Ch R = 1 ,1474    ,67.1,66,64.7
XS GIS Cut Line= 3
2170925.52826565765520.1501923872171217.31437621765458.123803616
2171292.44493162765391.729359297
#Sta/Elev= 30
       0 1096.63     6.8 1095.53    19.1 1094.56    33.5 1092.86    39.5  1091.9
    55.3 1088.91    72.2 1086.44    84.5 1086.17   121.3 1086.09   141.7 1086.45
     154  1086.1   173.4 1086.26   215.4 1085.62   227.6 1085.87   235.8 1085.54
   239.9 1085.09   242.81084.432   244.2 1084.14   247.6 1084.02   250.11084.401
   256.2 1085.43   268.5 1085.92   272.6 1086.52   276.7 1087.58   280.8 1088.12
     342    1091   376.9 1094.22   384.3 1094.49   394.5 1095.73   398.6 1096.02
#Mann= 3 ,-1,0
       0     .05       0   242.8    .045       0   250.1     .05       0
Bank Sta=242.8,250.1
XS Rating Curve= 0 ,0
Exp/Cntr(USF)=0,0
Exp/Cntr=0.3,0.1

Type RM Length L Ch R = 1 ,1408    ,26.7,27,27.3
XS GIS Cut Line= 3
 2170962.0647484765609.2573877052171254.45305038765506.785800839
2171280.81565648765450.158187161
#Sta/Elev= 30
       0 1090.83    10.7 1089.35    17.4 1088.68    48.9 1087.22    65.8 1086.59
      99 1086.27   109.1 1085.58   112.4 1085.57   121.2 1085.93     143 1085.34
   146.3 1085.16   150.6 1085.17   163.3 1085.59   171.8 1085.73   184.5 1085.66
   205.7 1085.25   217.9 1085.44   222.6 1085.18   224.91084.724   226.9 1084.28
   231.1 1083.91     234 1084.64   235.4 1084.95   239.6 1085.32   248.1 1085.48
   266.3 1086.15   281.1 1086.38   309.8 1087.48   332.9 1088.59   372.3 1091.34
#Mann= 3 ,-1,0
       0     .05       0   224.9    .045       0     234     .05       0
Bank Sta=224.9,234
XS Rating Curve= 0 ,0
Exp/Cntr(USF)=0,0
Exp/Cntr=0.3,0.1

Type RM Length L Ch R = 1 ,1381    ,217.7,221.5,222.2
XS GIS Cut Line= 3
2170958.23200733765631.463527883 2171304.5694331765521.590965226
2171352.34011252 765477.00499777
#Sta/Elev= 30
       0 1092.61    14.6 1090.06      23 1088.77    31.4 1087.93    39.8 1087.53
    60.8 1086.81    77.6 1086.53   113.4 1086.44   127.6 1086.09   157.3 1086.35
   174.1 1086.16   199.3 1085.58   210.4  1085.1   232.8 1084.96   237.31083.933
   241.2 1083.11   242.3 1083.19   246.21083.905   249.6 1084.72   258.2 1085.19
   295.8 1085.44   312.4 1086.25   329.4 1086.39   333.6 1086.61   346.1 1087.99
   350.6 1088.28   375.7  1089.4   399.1 1090.91   417.5  1091.5   428.7 1092.33
#Mann= 3 ,-1,0
       0     .05       0   237.3    .045       0   246.2     .05       0
Bank Sta=237.3,246.2
XS Rating Curve= 0 ,0
Exp/Cntr(USF)=0,0
Exp/Cntr=0.3,0.1

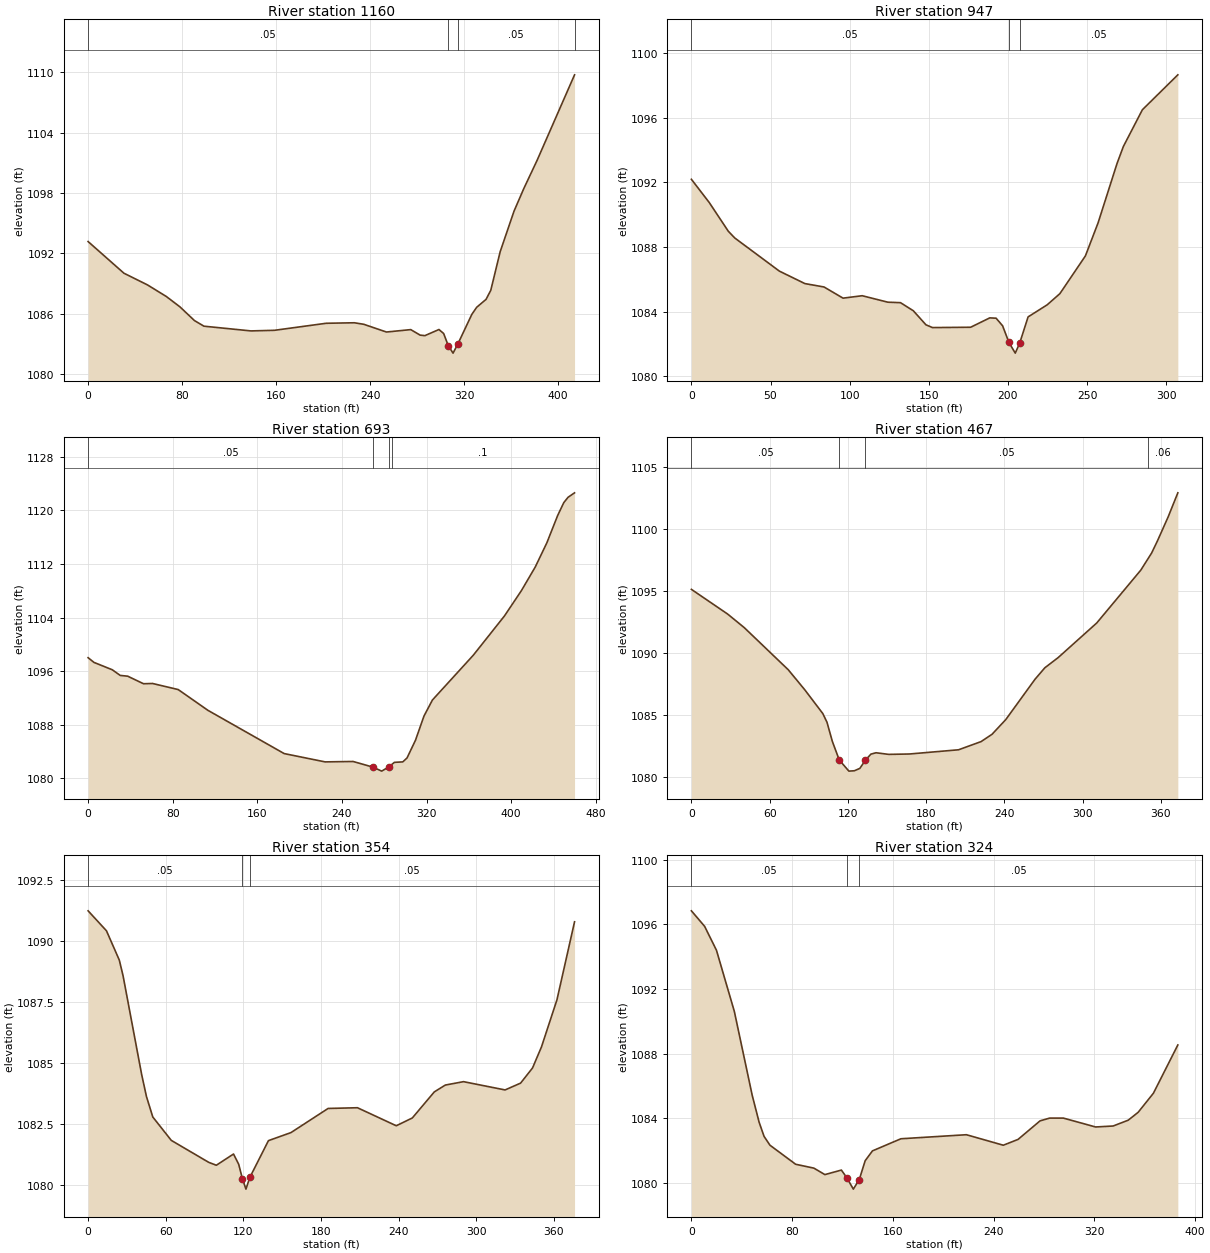
Type RM Length L Ch R = 1 ,1160    ,212.2,212.8,211.6
XS GIS Cut Line= 2
 2170981.6660012765703.9370991672171395.46983397765691.802089408
#Sta/Elev= 30
       0 1093.17    30.5 1090.02    50.5 1088.86    66.5 1087.71    78.1 1086.68
    90.5 1085.31    98.6 1084.75   138.6 1084.28   158.6 1084.34   202.6 1085.04
   226.6 1085.09   234.6 1084.94   253.9 1084.17   274.6 1084.41   282.6 1083.86
   286.6 1083.81   298.6 1084.42   302.6 1084.02   306.6 1082.79   310.6 1082.07
   314.6 1082.96   326.6 1085.93   330.7 1086.63   338.7 1087.42   342.7 1088.32
   350.7 1092.16   362.5  1096.2   370.8 1098.44   382.2 1101.27     414 1109.76
#Mann= 4 ,-1,0
       0     .05       0   306.6    .045       0   314.6     .05       0
  413.98     .06       0
Bank Sta=306.6,314.6
XS Rating Curve= 0 ,0
Exp/Cntr(USF)=0,0
Exp/Cntr=0.3,0.1

Type RM Length L Ch R = 1 ,947     ,250.9,253.6,255.5
XS GIS Cut Line= 3
2171040.99104511765896.4919818332171283.46604017765867.640966237
2171346.56809091765867.863461345
#Sta/Elev= 30
       0 1092.19    11.3 1090.75    23.3 1088.98    27.4 1088.56    55.6 1086.51
    71.7 1085.74    83.8 1085.53    95.8 1084.84   107.9 1084.99   124.1 1084.59
   132.1 1084.56   140.2 1084.06   148.2 1083.19   152.3 1083.02   176.4 1083.04
   188.5 1083.62   192.5  1083.6   196.6 1083.13   200.6  1082.1   204.6 1081.44
   207.4 1082.06   212.7 1083.68   224.8 1084.43   232.8 1085.12   248.9 1087.45
   256.9 1089.49   268.9 1093.17   272.9 1094.22   284.9 1096.49   307.3 1098.65
#Mann= 3 ,-1,0
       0     .05       0   200.6    .045       0   207.4     .05       0
Bank Sta=200.6,207.4
XS Rating Curve= 0 ,0
Exp/Cntr(USF)=0,0
Exp/Cntr=0.3,0.1

Type RM Length L Ch R = 1 ,693     ,222.8,226.4,227.6
XS GIS Cut Line= 3
2171022.54896064766106.9648104282171085.92067827766085.391459746
 2171478.2859938766108.313144846
#Sta/Elev= 30
       0 1098.01     5.5 1097.31    22.8 1096.21    30.4 1095.36    37.4 1095.25
    52.4 1094.12    60.9 1094.16    85.2 1093.25   113.3 1090.15   185.4 1083.69
   224.1 1082.45   250.6 1082.51   269.5 1081.66   277.6 1081.07   284.7 1081.73
   289.6 1082.38   297.6 1082.45   301.6 1083.04   309.6 1085.69   317.6 1089.29
   325.6 1091.69   364.2 1098.37   393.8 1104.26   409.8 1108.04   422.8 1111.54
   433.8 1115.16     444 1119.23   449.8 1121.16   453.9 1121.97     460 1122.63
#Mann= 4 ,-1,0
       0     .05       0   269.5    .045       0   284.7     .05       0
  286.94      .1       0
Bank Sta=269.5,284.7
XS Rating Curve= 0 ,0
Exp/Cntr(USF)=0,0
Exp/Cntr=0.3,0.1

Type RM Length L Ch R = 1 ,467     ,111.6,113,115.5
XS GIS Cut Line= 2
2171065.81271415766219.6374060452171419.07633157766339.639169214
#Sta/Elev= 30
       0 1095.14    27.8 1093.15    40.5 1092.06    74.3 1088.66      87 1087.04
   100.8 1085.13     104 1084.43   108.1 1082.89   113.4 1081.39   120.8 1080.49
     125 1080.52   129.2 1080.71   133.5 1081.38   137.7 1081.86   141.6 1081.97
   151.3 1081.84   167.2 1081.87   204.9 1082.21   222.2 1082.87   230.6 1083.46
   241.1 1084.64   263.6  1087.9   271.1 1088.82   281.3 1089.64   310.9 1092.43
   344.7 1096.69     353 1098.07   357.4 1099.03   365.8 1101.01   373.1 1102.92
#Mann= 4 ,-1,0
       0     .05       0   113.4    .045       0   133.5     .05       0
     350     .06       0
Bank Sta=113.4,133.5
XS Rating Curve= 0 ,0
Exp/Cntr(USF)=0,0
Exp/Cntr=0.3,0.1

Type RM Length L Ch R = 1 ,354     ,29.9,30.1,30.2
XS GIS Cut Line= 4
2171054.66277301766293.3128219092171205.14041318766393.631248684
2171286.74155423766481.5235358852171361.71605222766475.860829991
#Sta/Elev= 30
       0 1091.24    14.2 1090.42    24.1 1089.22      27 1088.58    41.4 1084.52
    45.1 1083.62      50 1082.78    64.3 1081.82    93.2 1080.92    99.1  1080.8
   112.4 1081.26   116.4 1080.84   119.3 1080.24     122 1079.82     125  1080.3
   139.4 1081.81   156.8 1082.14   185.5 1083.13   208.2 1083.16   238.2 1082.42
   250.6 1082.74   267.6 1083.81   276.1 1084.09   290.2 1084.23   322.3 1083.89
   334.3 1084.17   343.5 1084.79   350.4 1085.65   362.4 1087.59     376 1090.79
#Mann= 3 ,-1,0
       0     .05       0   119.3    .045       0     125     .05       0
Bank Sta=119.3,125
XS Rating Curve= 0 ,0
Exp/Cntr(USF)=0,0
Exp/Cntr=0.3,0.1

Type RM Length L Ch R = 1 ,324     ,269.9,260.7,249.3
XS GIS Cut Line= 4
2171035.31564785766319.8255489862171199.40793165766423.010216525
2171286.27141909766515.8434012142171351.55135929766518.157156744
#Sta/Elev= 30
       0 1096.84    10.5 1095.88    19.9  1094.4    34.1 1090.61    48.3 1085.41
    53.8 1083.74    57.7 1082.87    62.4 1082.32    82.8 1081.14    97.3  1080.9
     106  1080.5   119.1 1080.78   123.4 1080.31   128.6  1079.6   133.3 1080.19
     138 1081.36   143.8 1081.97   166.4 1082.72   218.4 1082.97   247.7 1082.32
   259.4 1082.68   276.9 1083.83   284.5    1084   295.4    1084     321 1083.45
   334.9 1083.51   346.9 1083.87   354.8 1084.36   366.9 1085.54   386.3 1088.53
#Mann= 3 ,-1,0
       0     .05       0   123.4    .045       0   133.3     .05       0
Bank Sta=123.4,133.3
XS Rating Curve= 0 ,0
Exp/Cntr(USF)=0,0
Exp/Cntr=0.3,0.1

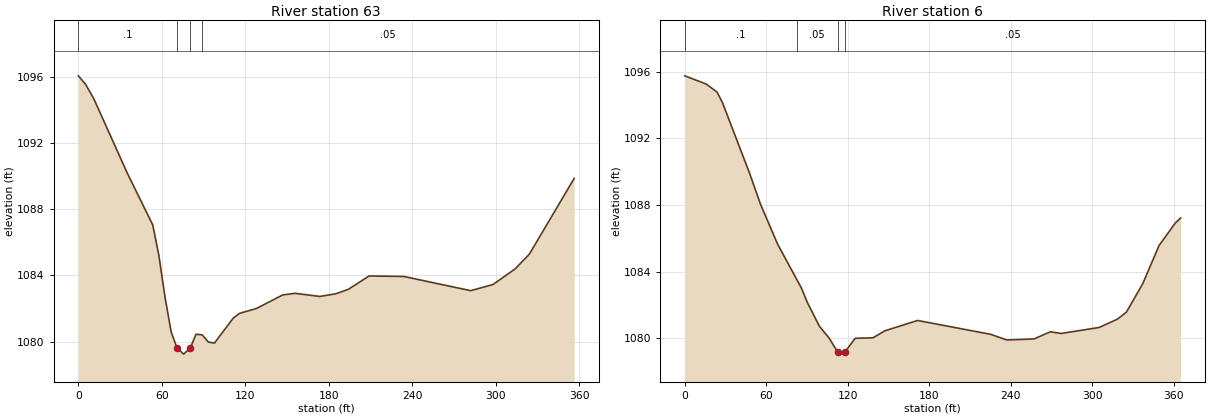
Type RM Length L Ch R = 1 ,63      ,57.1,57.1,57.1
XS GIS Cut Line= 4
2171025.24310435766624.5593338442171063.07273678766615.515886362
2171223.24365523 766537.627602762171362.52548371766529.029959026
#Sta/Elev= 30
       0 1096.08     5.2 1095.57    11.2 1094.68    35.1 1090.21    53.5 1087.06
    57.9 1085.22    62.4 1082.65    66.8 1080.57    70.9 1079.63    75.7 1079.24
    80.51079.614    84.6 1080.44      89 1080.41    93.5 1079.97    97.9 1079.91
   111.3 1081.41   115.7  1081.7   128.3 1082.01   146.9 1082.82   155.8 1082.92
   173.6 1082.73   185.1 1082.89   194.1 1083.16   209.1 1083.97     234 1083.94
   282.1 1083.08   298.1 1083.45   314.1  1084.4   324.3 1085.29   356.5 1089.87
#Mann= 4 ,-1,0
       0      .1       0    70.9    .045       0    80.5      .1       0
    88.9     .05       0
Bank Sta=70.9,80.5
XS Rating Curve= 0 ,0
Exp/Cntr(USF)=0,0
Exp/Cntr=0.3,0.1

Type RM Length L Ch R = 1 ,6       ,,,
XS GIS Cut Line= 4
2171020.45318422 766666.982472432171082.66573428766666.053926907
2171178.30592317766622.8765600762171376.08611962766622.412287315
#Sta/Elev= 30
       0 1095.76    15.7 1095.27    23.7 1094.79    27.7 1094.16    47.7 1089.91
    55.7 1088.06    68.3 1085.66    85.8 1083.03    90.2 1082.16      99 1080.74
   106.4    1080   112.4  1079.2   115.4 1079.06   118.11079.206   125.3 1080.01
   138.5 1080.04   147.3 1080.46   171.3 1081.08     225 1080.25     237 1079.91
     257 1079.97     269  1080.4     277  1080.3     305 1080.66   318.4 1081.16
     325 1081.58     337 1083.28     349 1085.57     361 1086.93   364.9 1087.23
#Mann= 4 ,-1,0
       0      .1       0   82.22     .05       0   112.4    .045       0
   118.1     .05       0
Bank Sta=112.4,118.1
XS Rating Curve= 0 ,0
Exp/Cntr(USF)=0,0
Exp/Cntr=0.3,0.1
LCMann Table=0

Chan Stop Cuts=-1
Use User Specified Reach Order=0
Composite Channel Slope=5